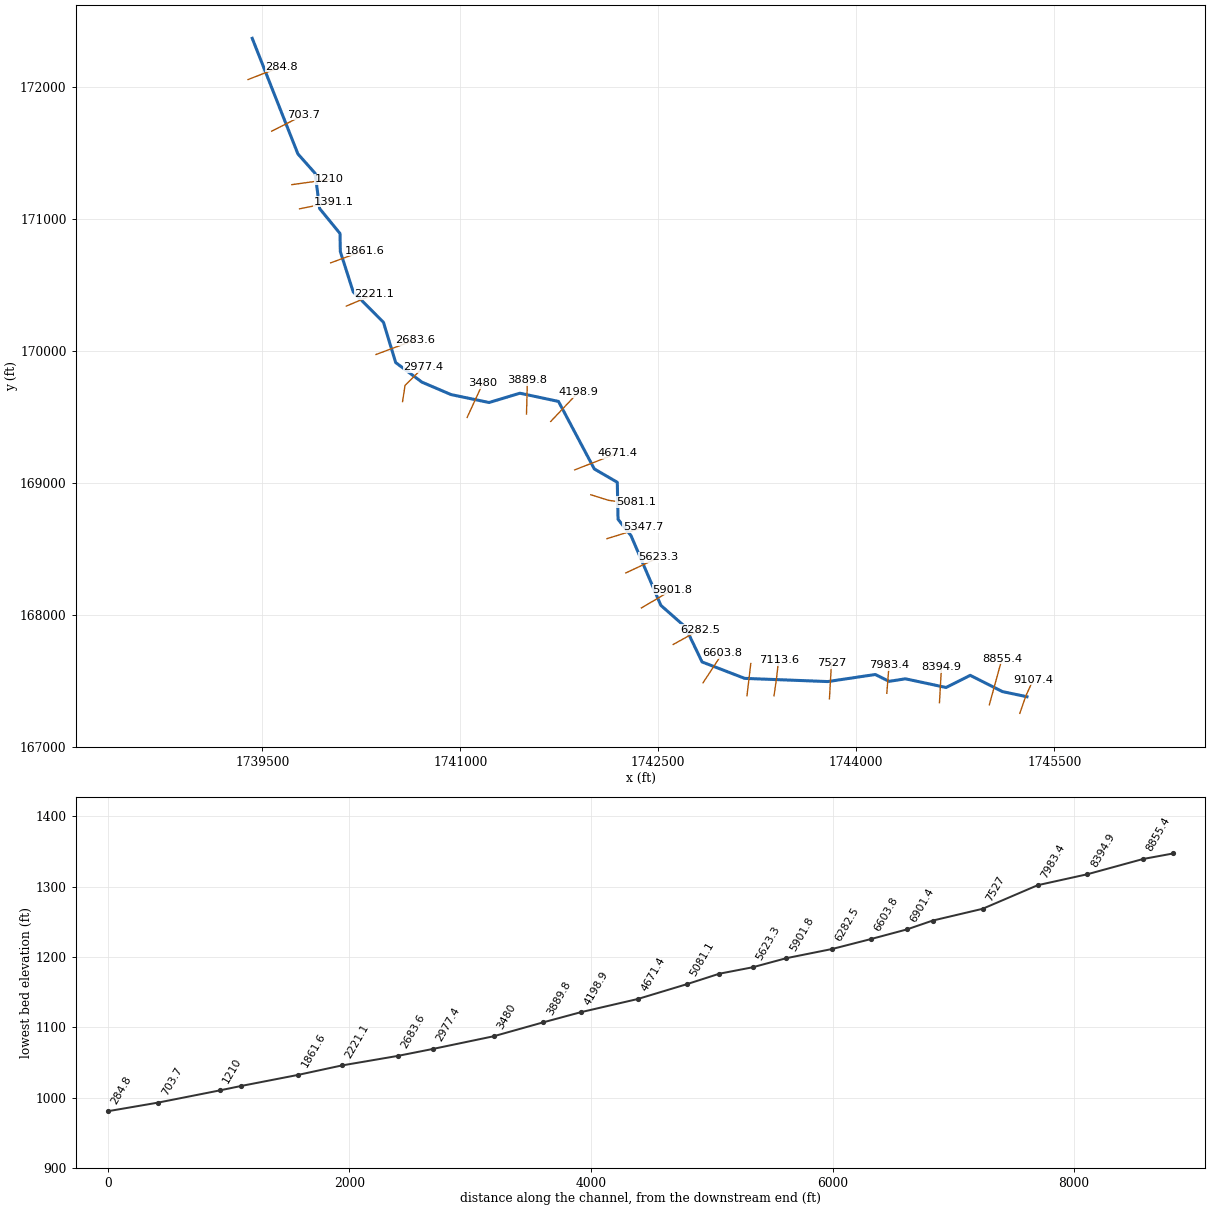
--- Harman Branch.prj (project) ---

Proj Title=Harman Branch
Current Plan=p01
Default Exp/Contr=0,0
English Units
Geom File=g01
Flow File=f01
Plan File=p01
BEGIN DESCRIPTION:
END DESCRIPTION:
DSS Export Rating Curves= 0
DSS Export Rating Curve Sorted= 0
DSS Export Volume Flow Curves= 0
DXF OffsetX= 0
DXF OffsetY= 0
DXF ScaleX= 0
DXF ScaleY= 0

--- Harman Branch.p01 (plan) ---

Plan Title=Floodplain
Program Version=4.00
Geom File=g01
Flow File=f01
K Sum by GR=0
Std Step Tol=0.01
Critical Tol=0.01
Num of Std Step Trials=20
Max Error Tol=0.3
Flow Tol Ratio=0.001
Split Flow NTrial=30
Split Flow Tol=0.02
Split Flow Ratio=0.02
Log Output Level=0
Friction Slope Method=1
Unsteady Friction Slope Method=2
Unsteady Bridges Friction Slope Method=1
Global Log Level=0
CheckData=False
Run HTab=0
Run UNet=0
Run PostProcess=0
UNET Theta=0
UNET Theta Warmup=0
UNET ZTol=0
UNET ZSATol=0
UNET MxIter=0
UNET MaxInSteps=0
UNET DtIC=0
UNET DtMin=0
UNET MaxCRTS=0
UNET WFStab=0
UNET SFStab=0
UNET WFX=0
UNET SFX=0
UNET DSS MLevel=0
UNET DZMax Abort=0
UNET Convert EG Bridges=0
UNET Use Existing IB Tables=0
UNET Froude Limit=0
UNET Froude Power=0
Write IC File=0
Echo Input=False
Echo Output=False
Write Detailed=0

--- Harman Branch.f01 (steady flow) ---

Flow Title=NFF Regression Equation
Program Version=4.00
Number of Profiles=1
Profile Names=P100yr
River Rch & RM=Harman Branch,Main      ,9107.4
568.3197
River Rch & RM=Harman Branch,Main      ,8394.9
575.0668
River Rch & RM=Harman Branch,Main      ,6901.4
636.5693
River Rch & RM=Harman Branch,Main      ,6603.8
744.5310
River Rch & RM=Harman Branch,Main      ,4198.9
803.1978
River Rch & RM=Harman Branch,Main      ,3889.8
911.1627
River Rch & RM=Harman Branch,Main      ,2977.4
922.2556
River Rch & RM=Harman Branch,Main      ,2683.6
1289.711
River Rch & RM=Harman Branch,Main      ,284.8
1346.660
Boundary for River Rch & Prof#=Harman Branch,Main      ,1
Up Type=0
Dn Type=3
Dn Slope=0.033064

--- Harman Branch.g01 (geometry) ---

Geom Title=Geometry
Program Version=4.00

River Reach=Harman Branch   ,Main
Reach XY= 30
     1745292.775      167380.553     1745107.617      167419.374
     1744862.862       167542.65     1744680.445      167450.481
     1744372.124      167516.362     1744248.535      167496.978
     1744144.169       167548.99     1743783.909      167495.428
     1743154.545      167519.608     1742831.629      167644.063
     1742703.944      167910.043     1742518.967      168073.258
     1742293.346      168601.012     1742195.097      168724.838
     1742189.337      169005.184     1742015.241      169106.313
     1741743.746      169617.771     1741451.393      169680.003
     1741218.076      169609.543     1740930.241      169669.505
     1740709.181      169763.833     1740510.323      169912.453
     1740417.794      170217.096     1740188.533      170447.922
     1740090.966      170753.332     1740088.802      170889.691
     1739934.045      171079.078     1739900.762      171345.067
     1739769.549      171493.024     1739423.605      172368.546

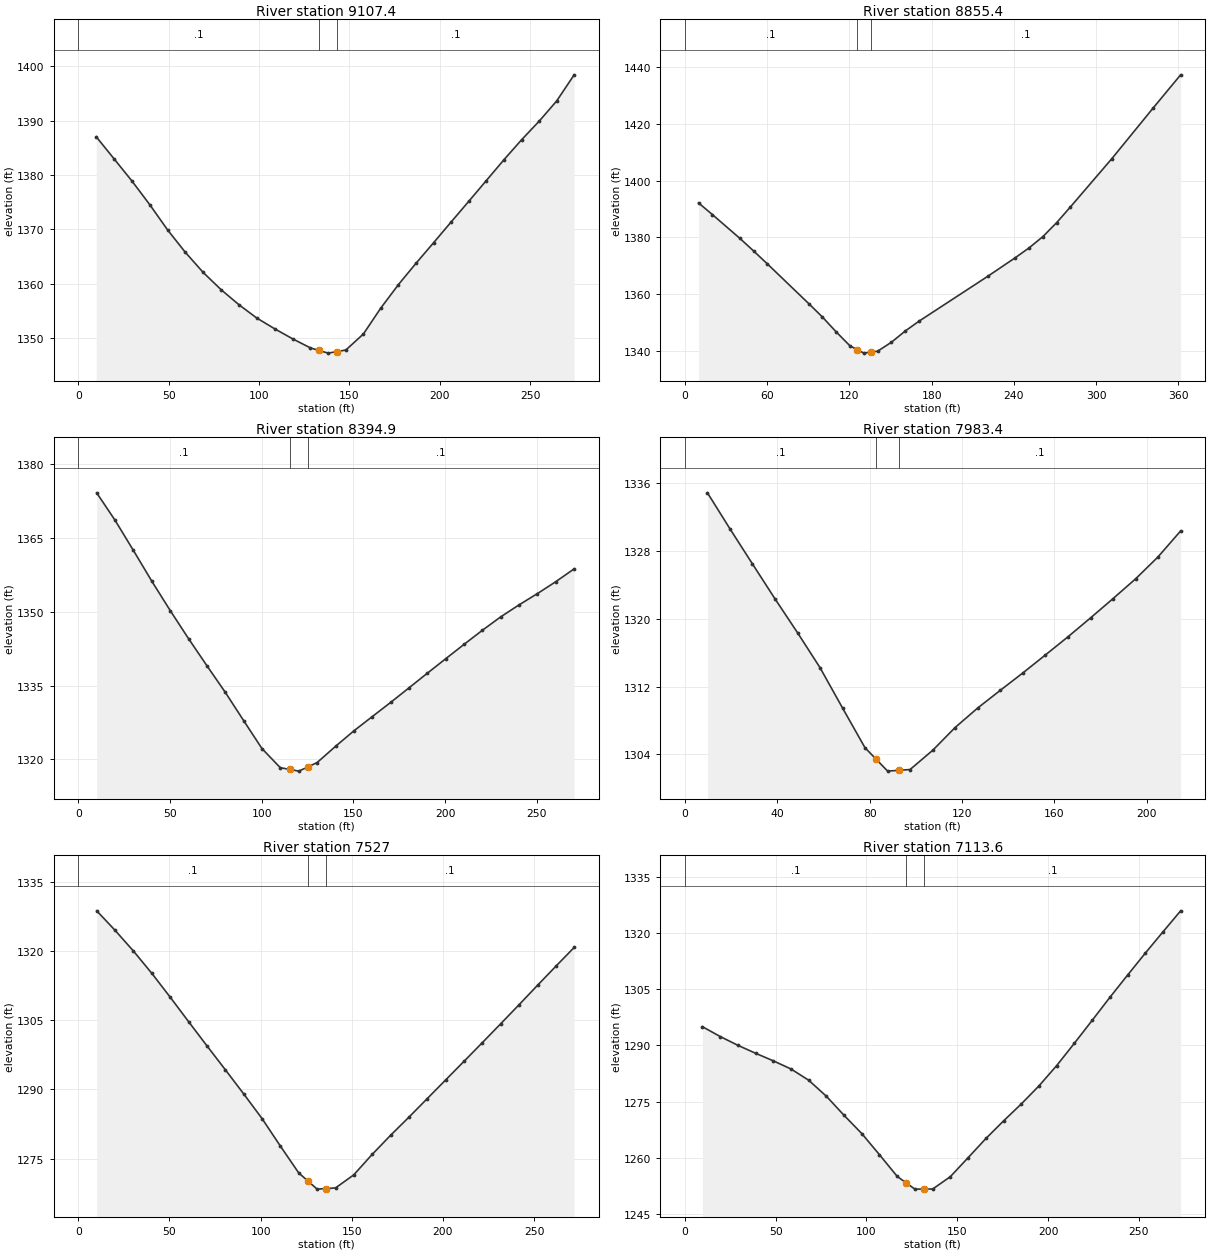
Type RM Length L Ch R = 1 ,9107.4  ,250.6,252,255.3
XS GIS Cut Line= 3
     1745238.748      167254.471     1745283.882      167385.125
     1745340.058      167509.108
#Sta/Elev= 30
     9.9 1387.05    19.7 1383.02    29.6 1378.94    39.5 1374.57    49.4 1369.91
    59.2  1365.8    69.1 1362.09      79 1358.92    88.9 1356.15    98.7 1353.72
   108.6 1351.74   118.5  1349.9   128.4 1348.22   133.2 1347.75   138.2 1347.26
   143.2 1347.55     148 1347.83   157.7 1350.78   167.4 1355.58   177.1 1359.87
   186.8 1363.78   196.6 1367.59   206.3  1371.4     216 1375.18   225.7 1378.99
   235.5 1382.84   245.2 1386.49   254.9  1389.9   264.6 1393.62   274.3 1398.44
#Mann= 3 , 0 , 0
       0      .1       0   133.2    .045       0   143.2      .1       0
Bank Sta=133.2,143.2
XS Rating Curve= 0 ,0
Exp/Cntr=0.3,0.1

Type RM Length L Ch R = 1 ,8855.4  ,455.9,460.5,465.1
XS GIS Cut Line= 2
     1745007.803      167319.435     1745103.644      167668.104
#Sta/Elev= 25
      10 1392.18    20.1 1388.07    40.2 1379.67    50.2 1375.24    60.3 1370.66
    90.4 1356.72   100.4 1351.98   110.5 1346.72   120.5 1341.83   125.6 1340.55
   130.6 1339.29   135.6 1339.63   140.6 1339.96   150.7 1343.12   160.7 1347.05
   170.8 1350.53     221 1366.35   241.1  1372.9   251.1 1376.34   261.2 1380.33
   271.2 1385.22   281.2 1390.73   311.4 1407.72   341.5 1425.53   361.6 1437.25
#Mann= 3 , 0 , 0
       0      .1       0   125.6    .045       0   135.6      .1       0
Bank Sta=125.6,135.6
XS Rating Curve= 0 ,0
Exp/Cntr=0.3,0.1

Type RM Length L Ch R = 1 ,8394.9  ,412,411.5,411
XS GIS Cut Line= 2
     1744630.029      167335.385     1744645.307      167605.294
#Sta/Elev= 29
      10 1374.23      20 1368.66      30 1362.53    40.1 1356.23    50.1 1350.28
    60.1 1344.56    70.1 1339.06    80.1 1333.66    90.1 1327.91   100.1 1322.21
   110.1 1318.32   115.2 1317.97   120.2 1317.62   125.2 1318.49   130.2 1319.37
   140.2 1322.66   150.2 1325.81   160.2  1328.7   170.2 1331.58   180.2 1334.54
   190.2 1337.52   200.3 1340.49   210.3 1343.41   220.3 1346.28   230.3 1349.01
   240.3 1351.45   250.3 1353.74   260.3 1356.16   270.3 1358.77
#Mann= 3 , 0 , 0
       0      .1       0   115.2    .045       0   125.2      .1       0
Bank Sta=115.2,125.2
XS Rating Curve= 0 ,0
Exp/Cntr=0.3,0.1

Type RM Length L Ch R = 1 ,7983.4  ,456.6,456.4,456.3
XS GIS Cut Line= 2
     1744231.106      167406.682     1744248.082      167620.572
#Sta/Elev= 24
     9.8 1334.89    19.5 1330.66    29.3 1326.49      39 1322.39    48.8 1318.37
    58.5 1314.26    68.3 1309.47      78 1304.79    82.8 1303.44    87.8 1302.03
    92.8 1302.13    97.5 1302.22   107.3 1304.49     117 1307.18   126.8 1309.49
   136.5 1311.56   146.3 1313.62     156 1315.73   165.8 1317.88   175.6 1320.12
   185.3 1322.39   195.1 1324.73   204.8 1327.32   214.6 1330.39
#Mann= 3 , 0 , 0
       0      .1       0    82.8    .045       0    92.8      .1       0
Bank Sta=82.8,92.8
XS Rating Curve= 0 ,0
Exp/Cntr=0.3,0.1

Type RM Length L Ch R = 1 ,7527    ,414.5,413.4,412.8
XS GIS Cut Line= 2
     1743796.535      167364.243     1743811.812       167635.85
#Sta/Elev= 29
    10.1 1328.66    20.2 1324.42    30.2 1319.97    40.3 1315.14    50.4 1309.97
    60.5 1304.67    70.5 1299.47    80.6 1294.29    90.7 1289.05   100.8 1283.69
   110.8 1277.77   120.9 1271.94     126 1270.17     131 1268.43     136 1268.56
   141.1 1268.69   151.1 1271.52   161.2 1275.95   171.3 1280.08   181.4 1284.02
   191.4 1288.02   201.5 1292.06   211.6  1296.1   221.7 1300.16   231.7 1304.22
   241.8 1308.35   251.9 1312.54     262 1316.68     272 1320.73
#Mann= 3 , 0 , 0
       0      .1       0     126    .045       0     136      .1       0
Bank Sta=126,136
XS Rating Curve= 0 ,0
Exp/Cntr=0.3,0.1

Type RM Length L Ch R = 1 ,7113.6  ,211.8,212.1,211.2
XS GIS Cut Line= 3
      1743376.81      167387.455     1743395.871      167522.608
      1743411.39       167658.28
#Sta/Elev= 30
     9.7    1295    19.5 1292.38    29.2 1290.04      39 1287.91    48.7  1285.9
    58.5 1283.71    68.2 1280.73      78 1276.43    87.7 1271.36    97.5 1266.47
   107.2 1260.85     117 1255.05   121.7 1253.42   126.7 1251.68   131.7  1251.7
   136.5 1251.71   146.2    1255     156 1260.07   165.8 1265.19   175.5 1269.87
   185.3 1274.41     195 1279.21   204.8 1284.65   214.5 1290.58   224.3 1296.69
     234 1302.79   243.8 1308.76   253.5 1314.59   263.3  1320.3     273  1325.9
#Mann= 3 , 0 , 0
       0      .1       0   121.7    .045       0   131.7      .1       0
Bank Sta=121.7,131.7
XS Rating Curve= 0 ,0
Exp/Cntr=0.3,0.1

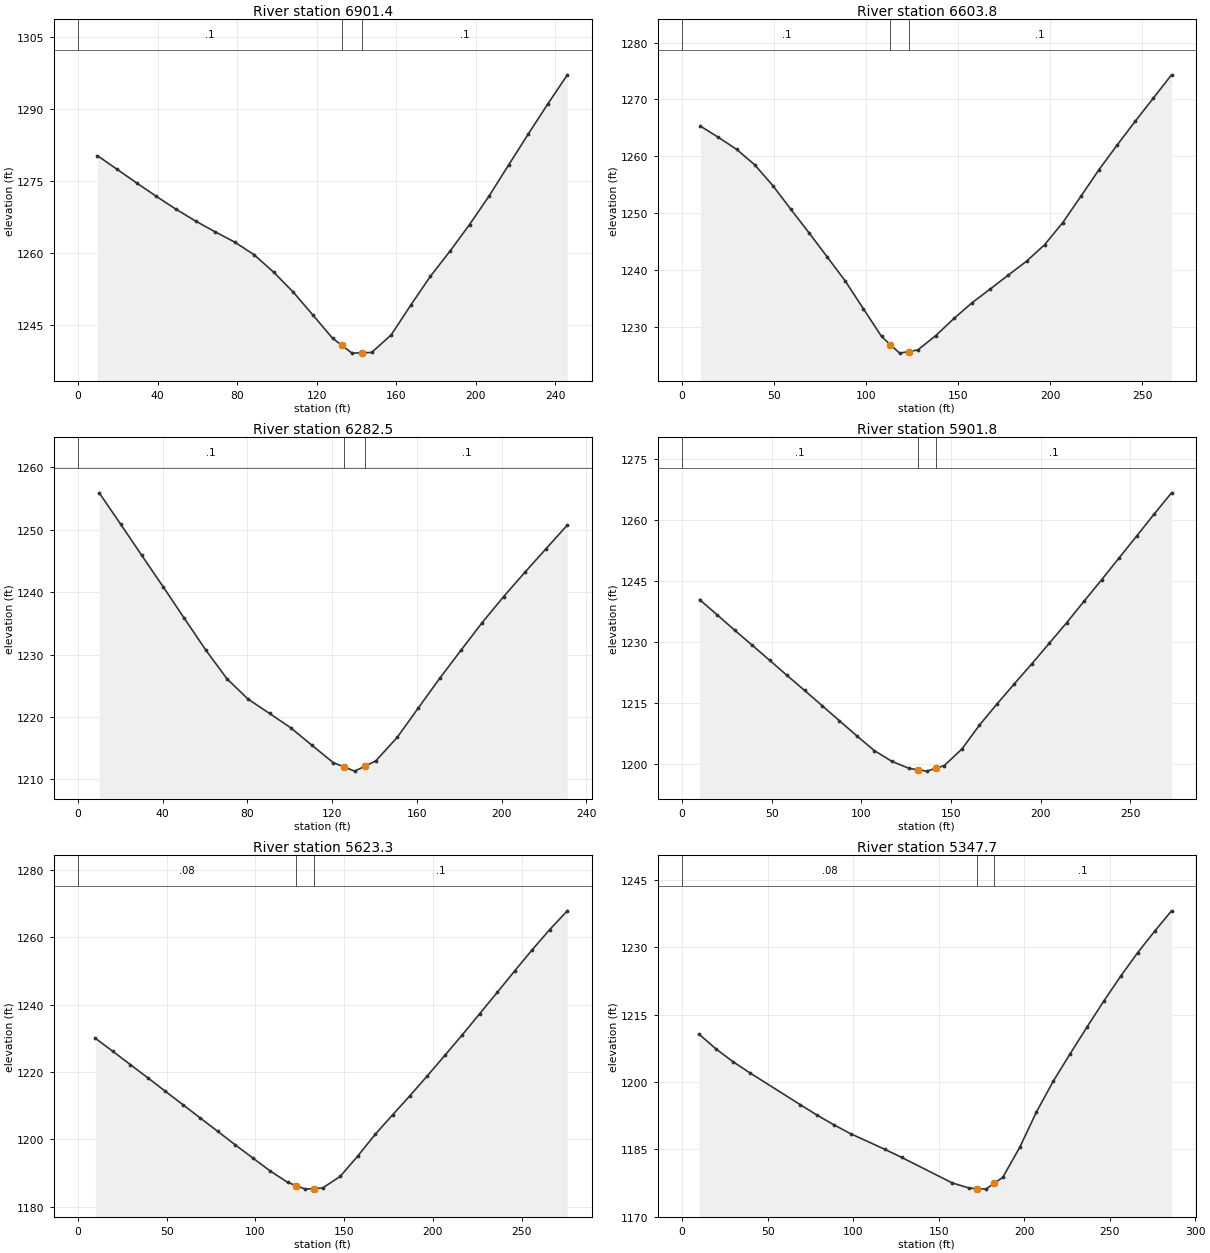
Type RM Length L Ch R = 1 ,6901.4  ,306.8,297.6,289.2
XS GIS Cut Line= 2
     1743171.838      167388.009     1743200.696      167632.455
#Sta/Elev= 27
     9.8 1280.23    19.7 1277.39    29.5 1274.56    39.4 1271.78    49.2 1269.12
    59.1 1266.65    68.9 1264.41    78.8 1262.27    88.6 1259.62    98.5 1255.97
   108.3 1251.84   118.1 1247.11     128 1242.28   132.8 1240.76   137.8 1239.17
   142.8 1239.24   147.7 1239.31   157.5 1242.96   167.4 1249.18   177.2 1255.13
   187.1 1260.39   196.9  1265.9   206.8 1271.88   216.6 1278.32   226.5 1284.77
   236.3 1291.01   246.1 1297.05
#Mann= 3 , 0 , 0
       0      .1       0   132.8    .045       0   142.8      .1       0
Bank Sta=132.8,142.8
XS Rating Curve= 0 ,0
Exp/Cntr=0.3,0.1

Type RM Length L Ch R = 1 ,6603.8  ,331.1,321.3,311.6
XS GIS Cut Line= 2
     1742839.119      167486.466     1742985.108      167708.845
#Sta/Elev= 29
     9.9 1265.33    19.7 1263.35    29.6 1261.24    39.4 1258.54    49.3 1254.87
    59.1  1250.7      69 1246.57    78.8 1242.37    88.7  1238.1    98.5 1233.26
   108.4 1228.38   113.2 1226.95   118.2 1225.46   123.2 1225.74   128.1 1226.02
   137.9 1228.55   147.8 1231.56   157.6 1234.31   167.5 1236.73   177.3 1239.17
   187.2  1241.6     197 1244.49   206.9 1248.39   216.8 1253.03   226.6 1257.69
   236.5 1262.02   246.3 1266.19   256.2 1270.27     266 1274.33
#Mann= 3 , 0 , 0
       0      .1       0   113.2    .045       0   123.2      .1       0
Bank Sta=113.2,123.2
XS Rating Curve= 0 ,0
Exp/Cntr=0.3,0.1

Type RM Length L Ch R = 1 ,6282.5  ,380.1,380.7,381.3
XS GIS Cut Line= 2
     1742613.346      167776.747     1742815.353      167888.784
#Sta/Elev= 25
      10 1255.92    20.1 1250.91    30.1 1245.89    40.2 1240.86    50.2  1235.8
    60.3 1230.73    70.3 1226.12    80.3 1222.85    90.4 1220.56   100.4 1218.26
   110.5 1215.44   120.5 1212.67   125.6 1211.99   130.6 1211.31   135.6 1212.13
   140.6 1212.96   150.7 1216.73   160.7 1221.46   170.7 1226.16   180.8 1230.69
   190.8 1235.12   200.9 1239.27   210.9 1243.16     221 1246.98     231 1250.75
#Mann= 3 , 0 , 0
       0      .1       0   125.6    .045       0   135.6      .1       0
Bank Sta=125.6,135.6
XS Rating Curve= 0 ,0
Exp/Cntr=0.3,0.1

Type RM Length L Ch R = 1 ,5901.8  ,280.4,278.5,276.7
XS GIS Cut Line= 3
      1742372.27      168053.502     1742489.972      168122.628
     1742607.674      168191.755
#Sta/Elev= 30
     9.7 1240.37    19.5 1236.63    29.2 1232.88      39 1229.18    48.8 1225.44
    58.5 1221.72    68.3 1218.03      78 1214.32    87.7 1210.58    97.5 1206.83
   107.2 1203.24     117 1200.58   126.7 1198.84   131.5 1198.52   136.5 1198.18
   141.5 1198.88   146.2 1199.54     156 1203.59   165.7 1209.41   175.5 1214.63
   185.2  1219.6     195 1224.54   204.7 1229.58   214.5 1234.68   224.2 1239.96
     234 1245.25   243.7  1250.6   253.5 1255.97   263.2 1261.34     273 1266.63
#Mann= 3 , 0 , 0
       0      .1       0   131.5    .045       0   141.5      .1       0
Bank Sta=131.5,141.5
XS Rating Curve= 0 ,0
Exp/Cntr=0.3,0.1

Type RM Length L Ch R = 1 ,5623.3  ,278.6,275.6,272.7
XS GIS Cut Line= 2
     1742253.466      168318.263     1742503.005      168435.394
#Sta/Elev= 30
     9.8 1230.01    19.7 1226.12    29.5  1222.2    39.4 1218.26    49.2 1214.29
    59.1 1210.32    68.9 1206.35    78.8 1202.37    88.6 1198.39    98.5 1194.49
   108.3 1190.63   118.1 1187.27     123 1186.27     128 1185.25     133 1185.43
   137.8 1185.59   147.7    1189   157.5    1195   167.4 1201.48   177.2 1207.26
   187.1 1213.02   196.9 1218.92   206.7 1224.94   216.6 1231.09   226.4 1237.36
   236.3  1243.7   246.1 1250.05     256 1256.34   265.8 1262.29   275.7 1267.84
#Mann= 3 , 0 , 0
       0     .08       0     123    .045       0     133      .1       0
Bank Sta=123,133
XS Rating Curve= 0 ,0
Exp/Cntr=0.3,0.1

Type RM Length L Ch R = 1 ,5347.7  ,275.4,266.6,257.8
XS GIS Cut Line= 2
     1742110.872      168577.988     1742384.177      168662.865
#Sta/Elev= 26
     9.9 1210.62    19.7 1207.36    29.6 1204.52    39.5 1202.03    69.1 1194.91
    78.9 1192.59    88.8 1190.42    98.7 1188.42   118.4    1185   128.3 1183.19
   157.9  1177.5   167.8 1176.35   172.6 1176.23   177.6 1176.11   182.6 1177.43
   187.5 1178.73   197.4  1185.4   207.2 1193.29   217.1  1200.2     227  1206.3
   236.8 1212.23   246.7 1218.05   256.6 1223.61   266.4 1228.77   276.3 1233.53
   286.2 1238.09
#Mann= 3 , 0 , 0
       0     .08       0   172.6    .045       0   182.6      .1       0
Bank Sta=172.6,182.6
XS Rating Curve= 0 ,0
Exp/Cntr=0.3,0.1

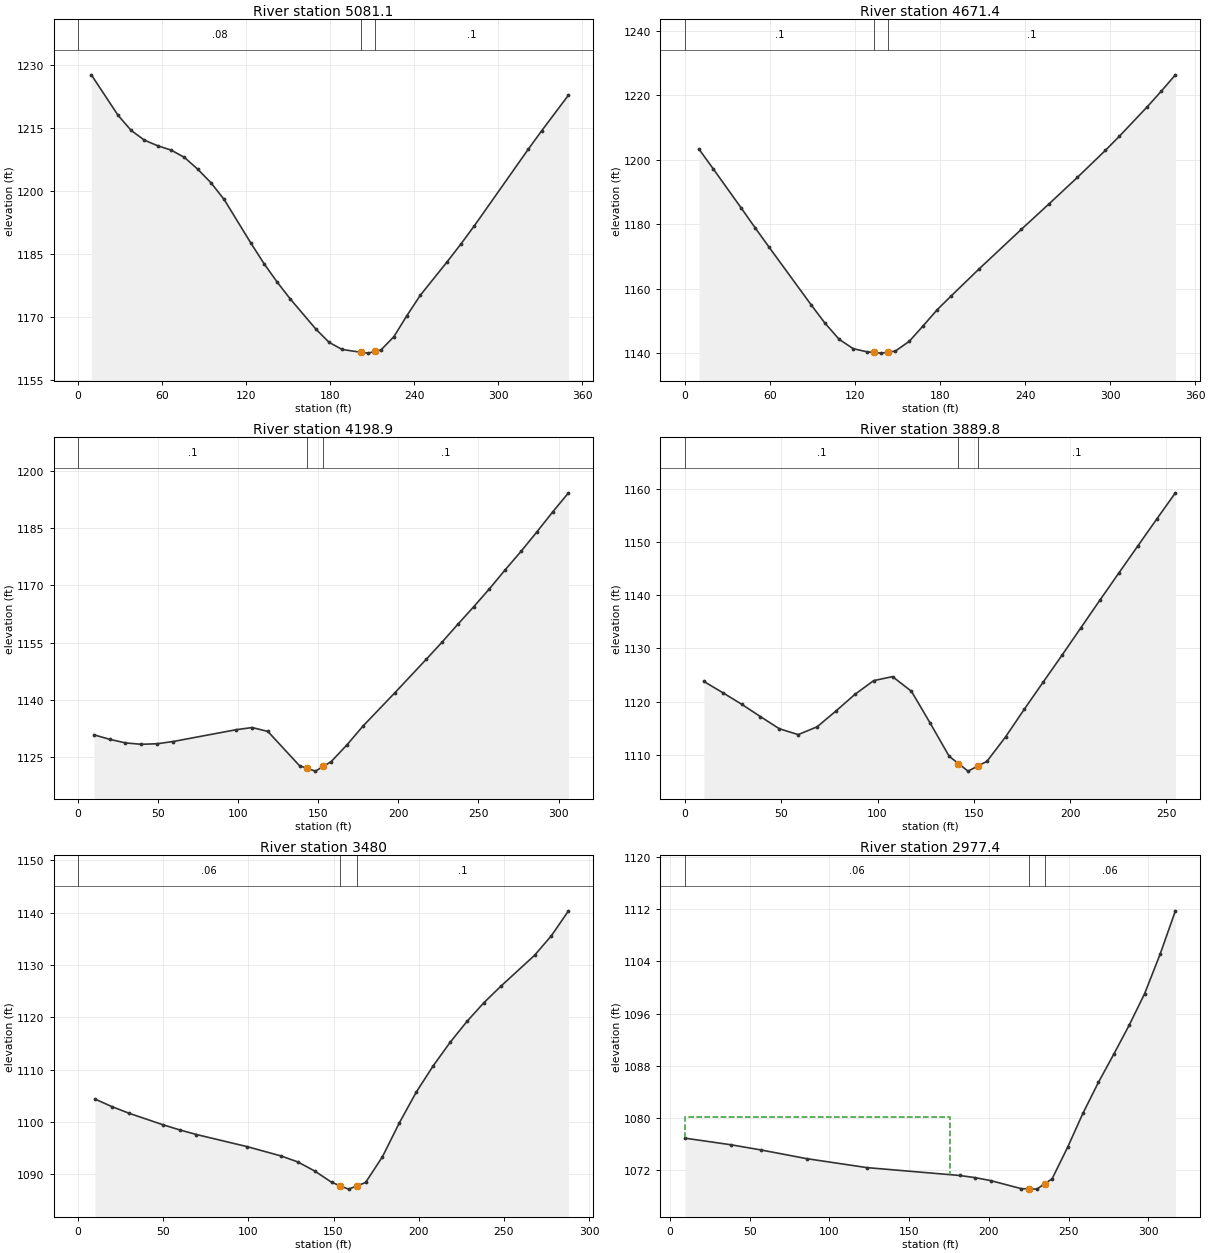
Type RM Length L Ch R = 1 ,5081.1  ,399.4,409.7,419.9
XS GIS Cut Line= 4
     1741988.649      168910.707     1742124.453      168868.268
      1742216.12      168856.385     1742331.553      168856.385
#Sta/Elev= 30
     9.5 1227.64    28.5 1218.02    37.9  1214.4    47.4 1212.07    56.9 1210.74
    66.4 1209.71    75.9 1207.98    85.4 1205.17    94.9 1201.92   104.3 1197.94
   123.3 1187.59   132.8 1182.64   142.3  1178.2   151.5 1174.24     170 1166.98
   179.3 1163.89   188.5 1162.21     202 1161.54     207 1161.34     212 1161.74
   216.2 1162.08   225.5 1165.28   234.7 1170.25   244.3 1175.11   263.6 1183.15
   273.2 1187.29   282.8 1191.63   321.3 1209.87   330.9 1214.28   350.1  1222.8
#Mann= 3 , 0 , 0
       0     .08       0     202    .045       0     212      .1       0
Bank Sta=202,212
XS Rating Curve= 0 ,0
Exp/Cntr=0.3,0.1

Type RM Length L Ch R = 1 ,4671.4  ,463.5,472.5,481.5
XS GIS Cut Line= 2
     1741866.426      169099.134     1742188.959      169224.752
#Sta/Elev= 27
     9.9 1203.29    19.8 1197.28    39.6 1185.11    49.4 1178.99    59.3 1172.95
      89 1155.07    98.9 1149.32   108.8 1144.36   118.7 1141.47   128.6 1140.47
   133.5 1140.28   138.5 1140.08   143.5 1140.39   148.3 1140.69   158.2  1143.7
   168.1 1148.56     178 1153.54   187.9 1157.82   207.7 1166.24   237.3 1178.41
   257.1 1186.41   276.9 1194.53   296.7 1202.92   306.6 1207.31   326.4 1216.51
   336.2  1221.3   346.1 1226.33
#Mann= 3 , 0 , 0
       0      .1       0   133.5    .045       0   143.5      .1       0
Bank Sta=133.5,143.5
XS Rating Curve= 0 ,0
Exp/Cntr=0.3,0.1

Type RM Length L Ch R = 1 ,4198.9  ,294.4,309.1,323.7
XS GIS Cut Line= 2
     1741684.788      169465.804     1741895.284      169688.182
#Sta/Elev= 27
     9.9  1130.8    19.8 1129.61    29.6 1128.68    39.5 1128.31    49.4 1128.46
    59.3 1129.04    98.8 1132.15   108.7 1132.71   118.5 1131.69   138.3 1122.68
   143.2 1121.98   148.2 1121.27   153.2 1122.53     158 1123.75   167.9 1128.17
   177.8 1133.05   197.6 1141.75   217.3 1150.58   227.2  1155.1   237.1 1159.81
   246.9 1164.36   256.8  1169.1   266.7 1174.12   276.6 1178.97   286.4 1184.03
   296.3 1189.28   306.2 1194.32
#Mann= 3 , 0 , 0
       0      .1       0   143.2    .045       0   153.2      .1       0
Bank Sta=143.2,153.2
XS Rating Curve= 0 ,0
Exp/Cntr=0.3,0.1

Type RM Length L Ch R = 1 ,3889.8  ,418,409.8,401.6
XS GIS Cut Line= 2
     1741501.453      169521.823     1741508.244      169776.455
#Sta/Elev= 28
     9.8 1123.78    19.6 1121.67    29.4  1119.5    39.2 1117.17      49 1114.89
    58.8 1113.79    68.6 1115.25    78.4 1118.22    88.2 1121.33      98 1123.93
   107.8 1124.68   117.6 1121.93   127.4 1115.92   137.2 1109.72     142 1108.36
     147 1106.93     152 1107.87   156.8 1108.76   166.5 1113.36   176.3  1118.6
   186.1 1123.69   195.9 1128.75   205.7  1133.9   215.5 1139.05   225.3 1144.13
   235.1 1149.18   244.9 1154.22   254.7  1159.2
#Mann= 3 , 0 , 0
       0      .1       0     142    .045       0     152      .1       0
Bank Sta=142,152
XS Rating Curve= 0 ,0
Exp/Cntr=0.3,0.1

Type RM Length L Ch R = 1 ,3480    ,509.9,502.7,495.4
XS GIS Cut Line= 2
     1741051.604       169496.36      1741172.13      169757.782
#Sta/Elev= 26
     9.9 1104.37    19.9 1102.92    29.8 1101.67    49.6 1099.48    59.6 1098.48
    69.5 1097.59    99.3 1095.27   119.1  1093.5     129 1092.35     139  1090.6
   148.9 1088.45   153.8  1087.8   158.8 1087.15   163.8 1087.78   168.8 1088.42
   178.7 1093.35   188.6 1099.81   198.5 1105.67   208.5 1110.73   218.4  1115.2
   228.3 1119.21   238.2 1122.77   248.2 1125.94     268 1131.85   277.9  1135.6
   287.9 1140.35
#Mann= 3 , 0 , 0
       0     .06       0   153.8    .045       0   163.8      .1       0
Bank Sta=153.8,163.8
XS Rating Curve= 0 ,0
Exp/Cntr=0.3,0.1

Type RM Length L Ch R = 1 ,2977.4  ,316,293.8,332.4
XS GIS Cut Line= 3
     1740562.711      169616.885     1740581.212      169739.234
     1740718.885      169874.912
#Sta/Elev= 21
     9.5 1076.92    38.1 1075.92    57.1 1075.12    85.7 1073.79   123.7 1072.41
   181.7 1071.21   191.4 1070.88   201.1 1070.43   220.4 1069.19   225.1 1069.16
   230.1 1069.12   235.1 1069.95   239.7 1070.71   249.4 1075.52     259 1080.72
   268.7 1085.45   278.4 1089.79     288 1094.21   297.7 1099.04   307.4 1105.07
     317 1111.72
#Mann= 3 , 0 , 0
     9.5     .06       0   225.1    .045       0   235.1     .06       0
#XS Ineff= 2 , 0
          175.59 1080.15
Permanent Ineff=
       F       F
Bank Sta=225.1,235.1
XS Rating Curve= 0 ,0
Exp/Cntr=0.3,0.1

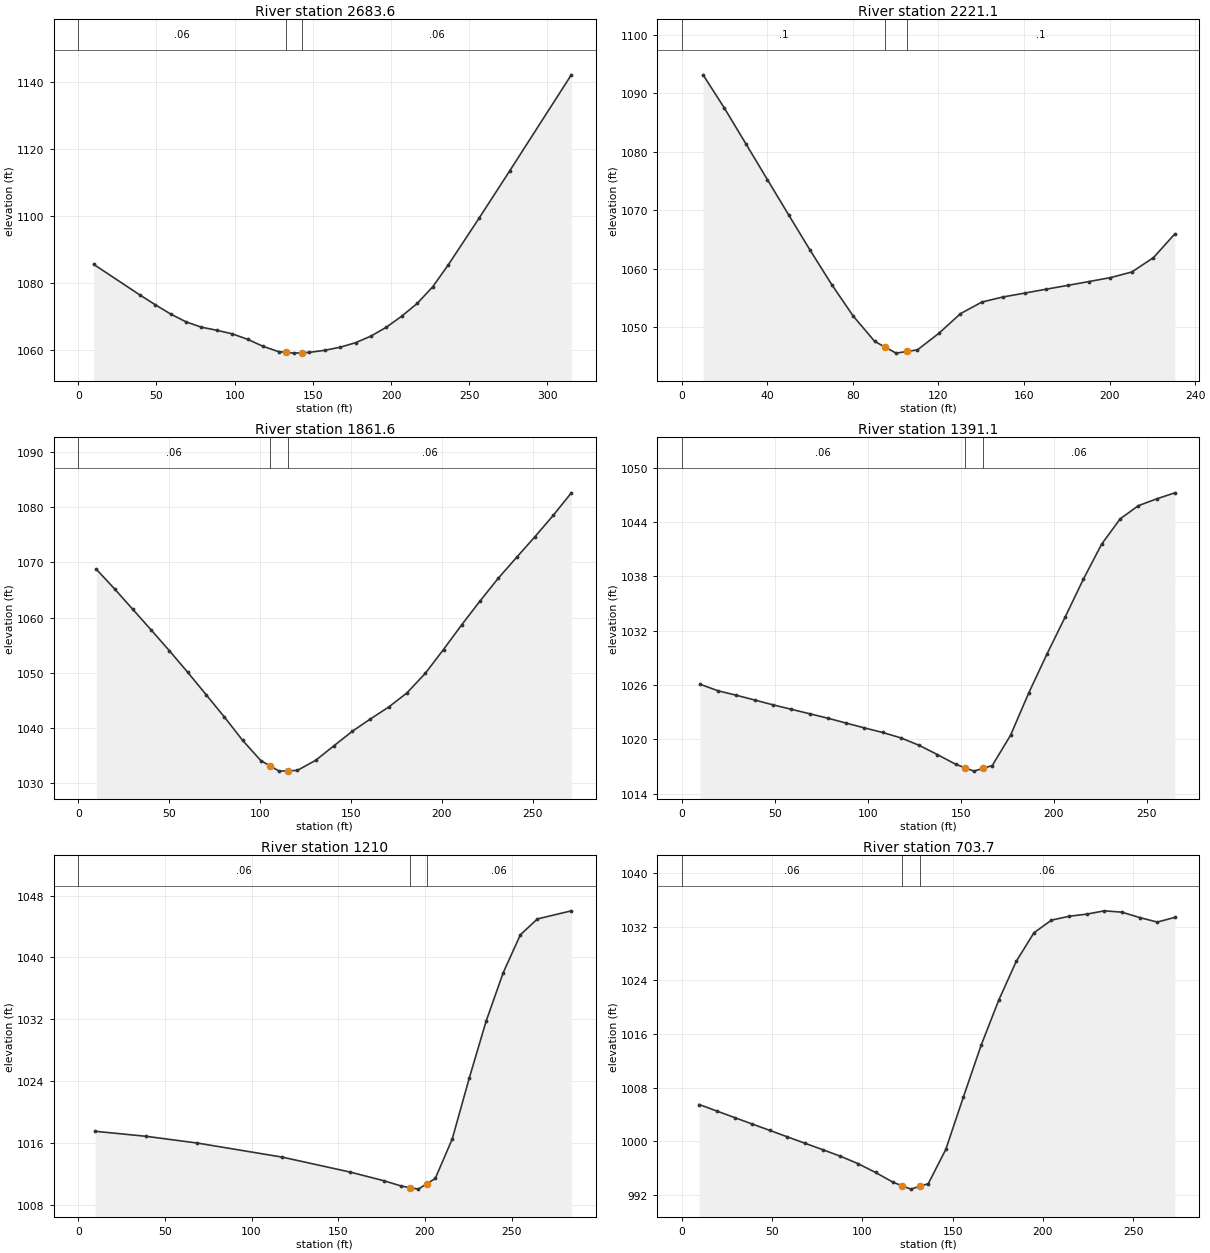
Type RM Length L Ch R = 1 ,2683.6  ,461.8,462.5,463.2
XS GIS Cut Line= 2
     1740361.489      169973.331     1740656.862      170083.672
#Sta/Elev= 27
     9.9 1085.58    39.4 1076.46    49.3 1073.53    59.1 1070.77      69 1068.42
    78.8 1066.84    88.7 1065.92    98.5 1064.86   108.4 1063.22   118.2 1061.13
   128.1 1059.56   132.9 1059.34   137.9 1059.11   142.9 1059.22   147.8 1059.33
   157.7 1059.96   167.5 1060.87   177.4 1062.23   187.2 1064.19   197.1 1066.86
   206.9 1070.14   216.8 1073.94   226.6 1078.85   236.5 1085.34   256.2 1099.26
   275.9 1113.45   315.3 1142.07
#Mann= 3 , 0 , 0
       0     .06       0   132.9    .045       0   142.9     .06       0
Bank Sta=132.9,142.9
XS Rating Curve= 0 ,0
Exp/Cntr=0.3,0.1

Type RM Length L Ch R = 1 ,2221.1  ,361,359.4,357.9
XS GIS Cut Line= 2
     1740136.627       170340.04      1740348.82      170430.009
#Sta/Elev= 25
      10 1093.17      20 1087.45    30.1 1081.31    40.1 1075.21    50.1 1069.14
    60.1 1063.12    70.1 1057.29    80.2 1051.88    90.2 1047.56    95.2 1046.55
   100.2 1045.55   105.2 1045.83   110.2 1046.11   120.2 1048.94   130.3  1052.3
   140.3 1054.29   150.3 1055.17   160.3 1055.82   170.4 1056.49   180.4 1057.14
   190.4  1057.8   200.4 1058.47   210.4 1059.43   220.5 1061.89   230.5 1065.95
#Mann= 3 , 0 , 0
       0      .1       0    95.2    .045       0   105.2      .1       0
Bank Sta=95.2,105.2
XS Rating Curve= 0 ,0
Exp/Cntr=0.3,0.1

Type RM Length L Ch R = 1 ,1861.6  ,473.1,470.5,468
XS GIS Cut Line= 2
     1740017.799      170667.666     1740272.431      170761.031
#Sta/Elev= 29
      10 1068.77    20.1 1065.19    30.1 1061.49    40.2 1057.75    50.2    1054
    60.3 1050.09    70.3 1046.08    80.4 1042.01    90.4  1037.8   100.4 1034.13
   105.5 1033.16   110.5 1032.21   115.5 1032.27   120.5 1032.34   130.6 1034.17
   140.6 1036.79   150.7 1039.41   160.7 1041.66   170.8 1043.83   180.8 1046.38
   190.9 1049.93   200.9 1054.24   210.9 1058.71     221 1063.03     231 1067.14
   241.1 1070.93   251.1 1074.64   261.2 1078.52   271.2 1082.62
#Mann= 3 , 0 , 0
       0     .06       0   105.5    .045       0   115.5     .06       0
Bank Sta=105.5,115.5
XS Rating Curve= 0 ,0
Exp/Cntr=0.3,0.1

Type RM Length L Ch R = 1 ,1391.1  ,182.4,181.1,179.8
XS GIS Cut Line= 2
      1739781.84      171076.774     1740041.565      171129.398
#Sta/Elev= 29
     9.8  1026.1    19.6 1025.37    29.4 1024.88    39.3 1024.35    49.1 1023.82
    58.9 1023.33    68.7 1022.84    78.5 1022.35    88.3 1021.81    98.1 1021.28
     108 1020.77   117.8 1020.17   127.6 1019.35   137.4 1018.33   147.2 1017.26
     152 1016.89     157  1016.5     162 1016.81   166.9 1017.12   176.7 1020.46
   186.5 1025.14   196.3 1029.44   206.1 1033.54   215.9 1037.73   225.7 1041.58
   235.6 1044.36   245.4 1045.82   255.2 1046.57     265 1047.24
#Mann= 3 , 0 , 0
       0     .06       0     152    .045       0     162     .06       0
Bank Sta=152,162
XS Rating Curve= 0 ,0
Exp/Cntr=0.3,0.1

Type RM Length L Ch R = 1 ,1210    ,499.4,506.3,513.2
XS GIS Cut Line= 2
     1739724.124      171260.109     1740005.916      171299.153
#Sta/Elev= 18
     9.8 1017.51    39.2 1016.86    68.7 1015.99   117.7 1014.17     157 1012.23
   176.6  1011.1   186.4 1010.43   191.2 1010.23   196.2 1010.03   201.2 1010.73
     206 1011.41   215.8 1016.52   225.6 1024.38   235.4 1031.79   245.2 1038.02
   255.1 1042.92   264.9 1044.97   284.5 1046.02
#Mann= 3 , 0 , 0
       0     .06       0   191.2    .045       0   201.2     .06       0
Bank Sta=191.2,201.2
XS Rating Curve= 0 ,0
Exp/Cntr=0.3,0.1

Type RM Length L Ch R = 1 ,703.7   ,420.9,418.9,416.7
XS GIS Cut Line= 3
     1739571.083      171665.185     1739692.855      171726.861
     1739814.626      171788.538
#Sta/Elev= 30
     9.7 1005.46    19.5 1004.48    29.3 1003.51      39 1002.55    48.8 1001.59
    58.5 1000.63    68.3  999.67      78  998.72    87.8  997.74    97.5  996.64
   107.3  995.31     117  993.85   121.8  993.35   126.8  992.82   131.8  993.24
   136.5  993.63   146.2  998.75     156 1006.63   165.8 1014.34   175.5 1021.04
   185.2 1026.84     195 1031.11   204.7    1033   214.5 1033.58   224.3  1033.9
     234 1034.39   243.7 1034.19   253.5 1033.39   263.3 1032.71     273 1033.41
#Mann= 3 , 0 , 0
       0     .06       0   121.8    .045       0   131.8     .06       0
Bank Sta=121.8,131.8
XS Rating Curve= 0 ,0
Exp/Cntr=0.3,0.1

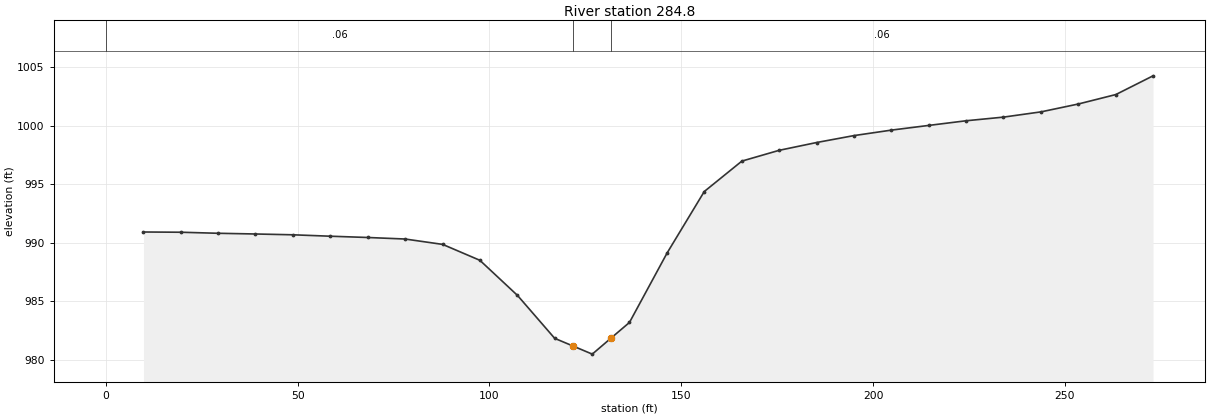
Type RM Length L Ch R = 1 ,284.8   ,290.5,284.8,279.3
XS GIS Cut Line= 3
     1739391.789      172056.115      1739518.97      172105.813
     1739647.244      172152.459
#Sta/Elev= 30
     9.8  990.91    19.5  990.89    29.3   990.8      39  990.74    48.8  990.67
    58.5  990.55    68.3  990.44      78  990.31    87.8  989.85    97.5  988.49
   107.3  985.49     117  981.82   121.8  981.16   126.8  980.47   131.8  981.87
   136.5  983.18   146.3  989.11     156  994.37   165.8  996.97   175.5  997.89
   185.3  998.56     195  999.15   204.8  999.62   214.5 1000.02   224.3 1000.42
     234 1000.73   243.8 1001.18   253.5 1001.85   263.3 1002.66     273 1004.26
#Mann= 3 , 0 , 0
       0     .06       0   121.8    .045       0   131.8     .06       0
Bank Sta=121.8,131.8
XS Rating Curve= 0 ,0
Exp/Cntr=0.3,0.1

Chan Stop Cuts=-1
Use User Specified Reach Order=0